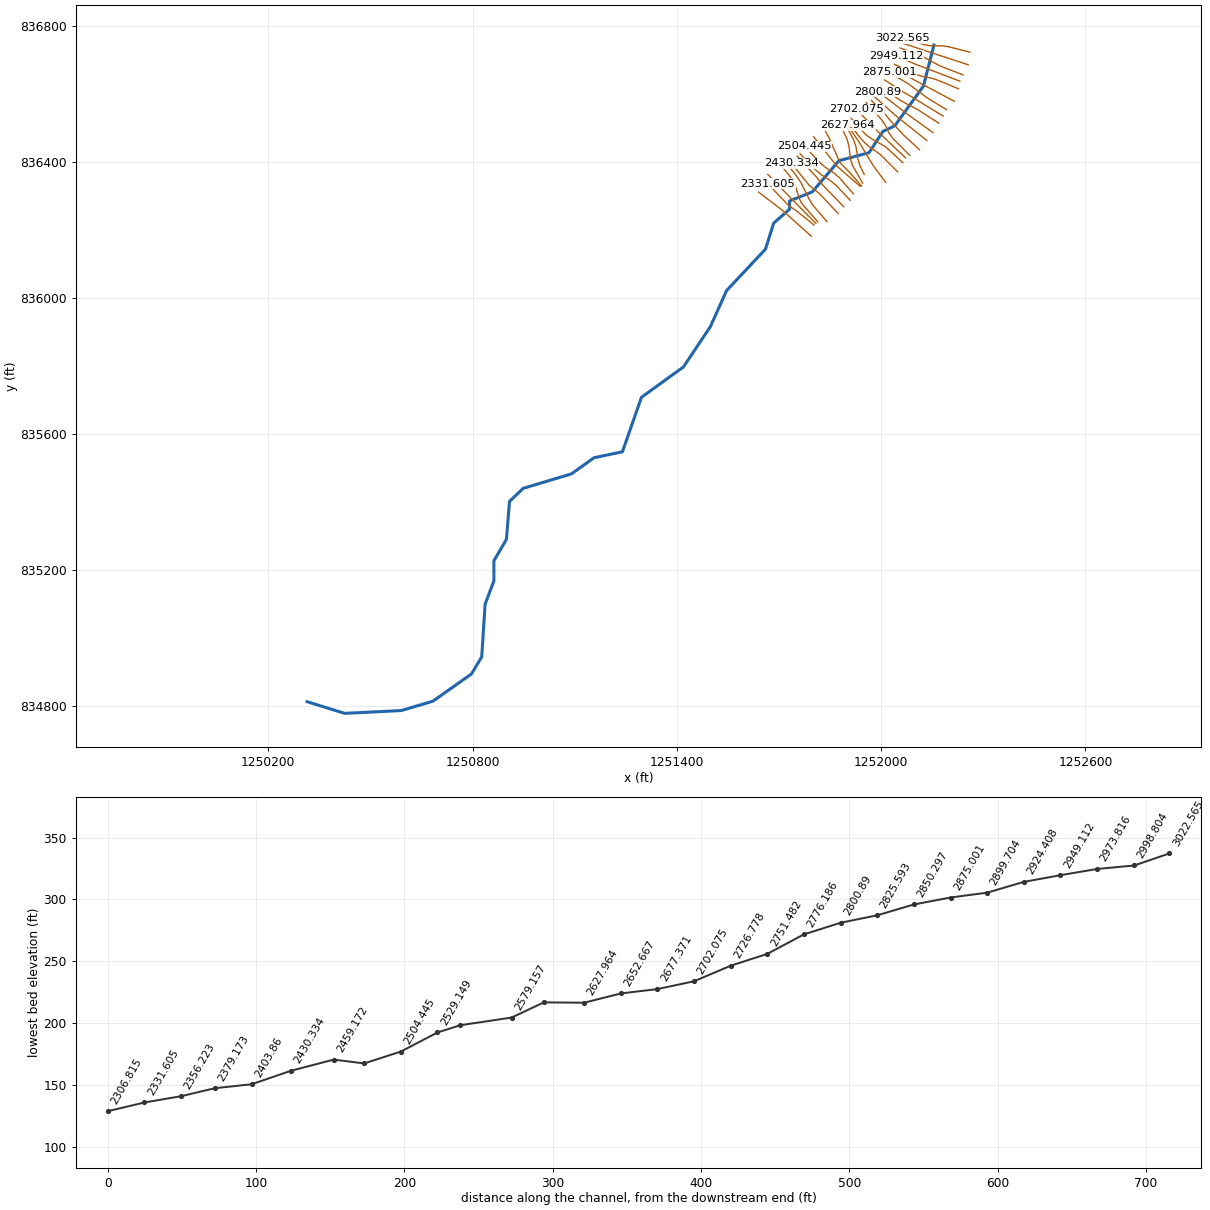
--- 72_ras.prj (project) ---

Proj Title=72
Current Plan=p01
Default Exp/Contr=0.3,0.1
English Units
Geom File=g01
Flow File=f01
Plan File=p01
Y Axis Title=Elevation
X Axis Title(PF)=Main Channel Distance
X Axis Title(XS)=Station
BEGIN DESCRIPTION:
RFD model 72 exported to HEC-RAS
END DESCRIPTION:

--- 72_ras.p01 (plan) ---

Plan Title=Plan 01
Program Version=4.10
Short Identifier=Plan 01
Geom File=g01
Flow File=f01
Subcritical Flow
Calc Critical at every XS
Secant Critical Depth

--- 72_ras.f01 (steady flow) ---

Flow Title=Flow 01
Program Version=5.01
Number of Profiles= 5
Profile Names=10yr,25yr,50yr,100yr,500yr
River Rch & RM=72,48,3022.565
  131.72   234.6  334.16  453.64  807.51
River Rch & RM=72,48,2702.075
  142.89  254.94  363.76  494.73  885.02
River Rch & RM=72,48,2579.157
   146.6  261.72  373.63  508.45  910.98
River Rch & RM=72,48,2479.741
  155.88  278.66  398.32  542.81  976.17
River Rch & RM=72,48,2331.605
  170.69  305.74  437.88  597.94 1081.26
River Rch & RM=72,48,2168.054
  172.54  309.13  442.82  604.84 1094.46
River Rch & RM=72,48,2078.701
  210.63  379.02  545.21  748.06 1370.12
River Rch & RM=72,48,1989.347
   224.7  404.92  583.26  801.44 1473.66
River Rch & RM=72,48, 1810.64
  228.98   412.8  594.85  817.71 1505.31
River Rch & RM=72,48,1737.093
  244.85  442.06  637.91  878.24 1623.32
River Rch & RM=72,48,1610.534
  260.69   471.3  681.01  938.91 1742.08
River Rch & RM=72,48,1427.325
  267.38  483.67  699.26  964.61 1792.54
River Rch & RM=72,48,1304.199
  269.81  488.17  705.89  973.97 1810.91
River Rch & RM=72,48,1113.455
   293.5     532  770.63 1065.33 1990.92
River Rch & RM=72,48,934.6901
  297.14  538.74   780.6  1079.4 2018.75
River Rch & RM=72,48,803.3347
  301.38   546.6  792.23 1095.84 2051.25
River Rch & RM=72,48,555.9908
  335.87   610.6  887.01 1229.95 2317.49
River Rch & RM=72,48,  346.76
  347.34  631.93  918.63 1274.77 2406.85
River Rch & RM=72,48,127.3899
  420.76  768.72 1121.99 1563.75 2987.05
Boundary for River Rch & Prof#=72,48,1
Up Type= 0
Dn Type= 2
Boundary for River Rch & Prof#=72,48,2
Up Type= 0
Dn Type= 2
Boundary for River Rch & Prof#=72,48,2
Up Type= 0
Dn Type= 2
Boundary for River Rch & Prof#=72,48,2
Up Type= 0
Dn Type= 2
Boundary for River Rch & Prof#=72,48,2
Up Type= 0
Dn Type= 2

--- 72_ras.g01 (geometry) ---

Geom Title=72
Program Version=4.10

River Reach=72,48
Reach XY= 30
1252154.90414336836742.7229910941252124.20215833836622.234148994
1252040.03551298836505.5675192481252005.03552279836488.900858521
1251964.20219964836426.4008781911251875.86889154 836403.06755434
1251797.53557849836311.4009170831251730.86893064836284.734260216
1251730.86892995836260.567600727 1251684.3877117836219.786417782
1251660.03561395836143.0676375481251545.69740942836021.204932943
 1251498.3689881835915.567709491 1251419.2023412835797.234413445
 1251295.8690415835708.0677767251251240.03571987835548.067825645
1251156.70241049835530.5678332451251090.03576195835483.067849264
1250948.36913568835440.5678659831250908.36914635835402.234545127
1250899.20247906835290.5679117441250862.53582132835228.067931265
1250862.53581962835168.9012820871250836.70249185835100.567969739
1250826.70249027834945.5680157991250796.70249763 834895.56803146
1250683.36919516834815.5680584461250590.86922157834788.068069249
1250424.20260361834779.7347432671250314.20263693834813.901403055

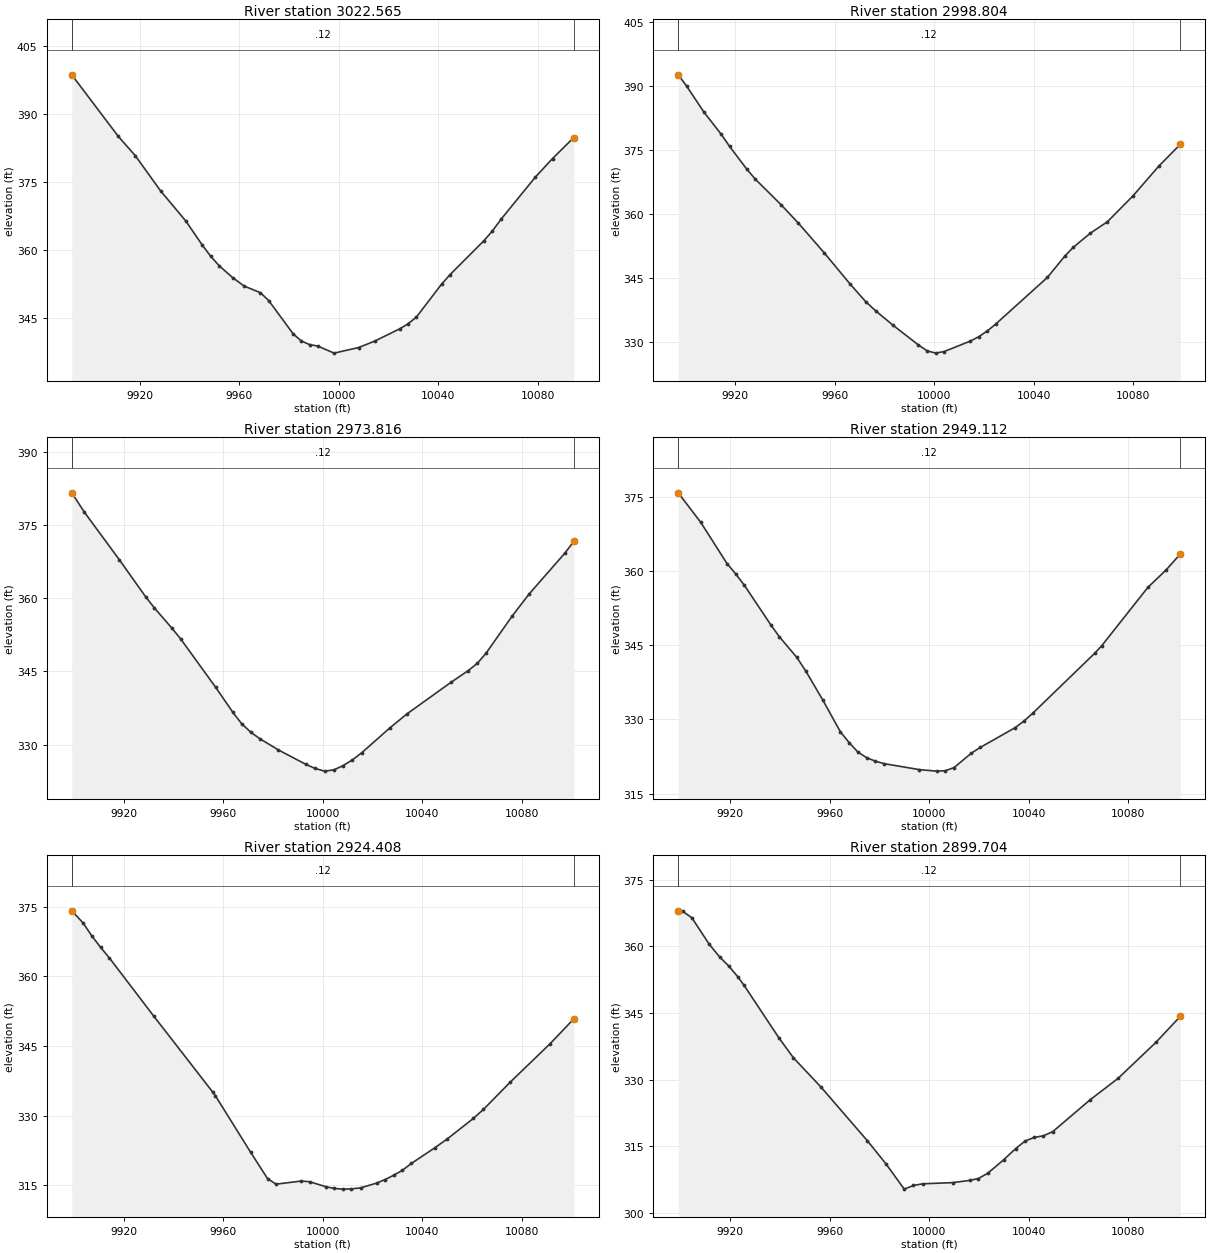
Type RM Length L Ch R = 1 ,3022.565,23.761100,23.761100,23.761100
XS GIS Cut Line= 6
1252260.54100623836721.8978689261252196.08620046836738.129330067
1252175.65645019836740.4379626971252146.55771702836740.563054911
1252127.49567169 836743.429693521252063.80947344836762.411041598
#Sta/Elev= 30
 9892.56398.56969911.285384.97649918.108380.73059928.333372.92929938.401366.3322
9945.113360.94879948.468358.50869951.824356.45769957.223 353.8389961.846351.9657
 9968.45350.48519971.751348.76499981.644341.38919984.924339.82739988.205339.0404
9991.486338.7179 9998.05337.156510007.89338.385610014.52339.834810024.47 342.525
10027.79343.610310031.18345.121410041.35352.414110044.74354.4975 10058.3361.9543
10061.72364.106110065.18366.680510079.02376.009610085.93380.104810094.49384.7381
#Mann= 3 , 0 , 0
 9892.56    0.12       0 9892.56    0.12       010094.49    0.12       0
#XS Ineff= 2 , 0
       09990.578                       0
Bank Sta=9892.56,10094.49
Exp/Cntr=0.3,0.1

Type RM Length L Ch R = 1 ,2998.804,24.988300,24.988300,24.988300
XS GIS Cut Line= 4
1252255.61623513836684.7531498731252160.59825466836715.886840618
1252158.72559632836716.5890875551252063.78214459836747.915285107
#Sta/Elev= 30
9897.007 392.5879900.417389.92069907.322383.86689914.227  378.71 9917.68375.7994
9924.585370.48499928.037368.12519938.394362.14279945.299357.85779955.657350.9295
9966.014 343.6579972.357339.47139976.372337.31769983.276333.97269993.634329.2848
9997.088327.925610000.57327.375710004.02327.754610014.39330.170410017.84331.2128
 10021.3332.553910024.75334.204310045.48345.101410052.39350.024410055.85352.1389
10062.76355.467410069.67358.170710080.03364.291410090.39 371.24410098.97 376.287
#Mann= 3 , 0 , 0
9897.007    0.12       09897.007    0.12       010098.97    0.12       0
#XS Ineff= 2 , 0
       09990.917                       0
Bank Sta=9897.007,10098.97
Exp/Cntr=0.3,0.1

Type RM Length L Ch R = 1 ,2973.816,24.703700,24.703700,24.703700
XS GIS Cut Line= 6
 1252240.7070042836655.0347993961252175.75734448836680.028322969
1252148.80736359836694.0058330611252147.14326303836695.115233506
1252125.07076838836707.1361206011252055.38907052836734.408639467
#Sta/Elev= 30
9899.048381.59299904.123377.62469918.184367.8753 9928.73360.31529932.245358.0243
9939.276353.89159942.792351.69769956.853341.79459963.884336.58799967.399334.2739
9971.031332.54789974.727 331.2059982.119328.92119993.206325.95779996.902325.1225
 10000.7324.573310004.46324.831110008.19325.710910011.93326.883610015.66328.3371
10026.83333.370610033.88336.310910051.49 342.74410058.54345.189910062.06346.6252
10065.58348.677610076.15356.3422 10083.1360.943510097.29 369.19710100.96371.6503
#Mann= 3 , 0 , 0
9899.048    0.12       09899.048    0.12       010100.96    0.12       0
#XS Ineff= 2 , 0
       09972.545                       0
Bank Sta=9899.048,10100.96
Exp/Cntr=0.3,0.1

Type RM Length L Ch R = 1 ,2949.112,24.703700,24.703700,24.703700
XS GIS Cut Line= 5
1252231.32619628836636.5003583791252137.93138096836672.197946869
 1252136.0744276836672.9407282761252098.19505819836687.342806364
1252043.59122662836710.894877084
#Sta/Elev= 30
9899.015375.90259908.092369.91289918.629361.57879922.141359.47639925.653357.1546
 9936.19349.21379939.703346.74049946.727 342.569 9950.24  339.889957.264333.8495
9964.289 327.4669967.801 325.294 9971.23323.42649974.826322.25019978.338321.5482
9981.851 321.052  9995.9319.847910002.94 319.53610006.45319.617110009.96320.2474
10016.98323.189810020.49324.327310034.52328.332110038.03329.651910041.55331.2267
10066.56343.406610069.37344.930710087.99356.777310095.14360.205810100.99 363.512
#Mann= 3 , 0 , 0
9899.015    0.12       09899.015    0.12       010100.99    0.12       0
#XS Ineff= 2 , 0
       09980.132                       0
Bank Sta=9899.015,10100.99
Exp/Cntr=0.3,0.1

Type RM Length L Ch R = 1 ,2924.408,24.703800,24.703800,24.703800
XS GIS Cut Line= 6
1252226.99341201836614.2686500861252162.60353146836641.009502976
1252145.90033589836645.9001693811252117.39371773 836651.44971951
1252101.95566474836656.4728726161252039.02827521836686.034961988
#Sta/Elev= 30
9899.031374.1478 9903.52371.57639907.072368.75879910.625366.27369914.177363.9752
 9931.94351.48189955.787335.01499956.807334.25479970.932322.10939977.769316.3992
9981.188315.20279991.324315.87099994.665 315.72710001.35 314.63110004.69314.2794
10008.03314.128910011.38314.1676 10015.2314.406110021.61315.422110025.06316.2042
10028.51317.121410031.98318.174610035.61319.6689 10045.1323.063310050.11324.9755
10060.53329.375310064.61331.323310075.48337.2552 10091.4345.481610100.96350.8601
#Mann= 3 , 0 , 0
9899.031    0.12       09899.031    0.12       010100.96    0.12       0
#XS Ineff= 2 , 0
       09986.669                       0
Bank Sta=9899.031,10100.96
Exp/Cntr=0.3,0.1

Type RM Length L Ch R = 1 ,2899.704,24.703700,24.703700,24.703700
XS GIS Cut Line= 4
1252214.55719267836577.6842901591252126.24659509836624.572812839
1252124.39723892836625.334312508   1252036.86562836673.597582225
#Sta/Elev= 30
9899.014368.0051 9900.77367.90879904.485366.44839911.508360.46479915.629357.6567
9919.343355.58839923.058353.1165  9925.5351.23939939.492339.44339945.346334.9418
9956.489 328.3249975.062316.30239982.492311.14729989.921305.40019993.635306.2266
 9997.35306.597710009.58306.867310016.37307.3741 10019.7307.784210023.45308.9402
10029.96312.027610034.69314.495410038.44316.184210042.18317.033510045.93317.4027
10049.68318.340510064.66325.4834 10075.9330.299410091.11338.393910100.96344.2687
#Mann= 3 , 0 , 0
9899.014    0.12       09899.014    0.12       010100.96    0.12       0
#XS Ineff= 2 , 0
       09989.563                       0
Bank Sta=9899.014,10100.96
Exp/Cntr=0.3,0.1

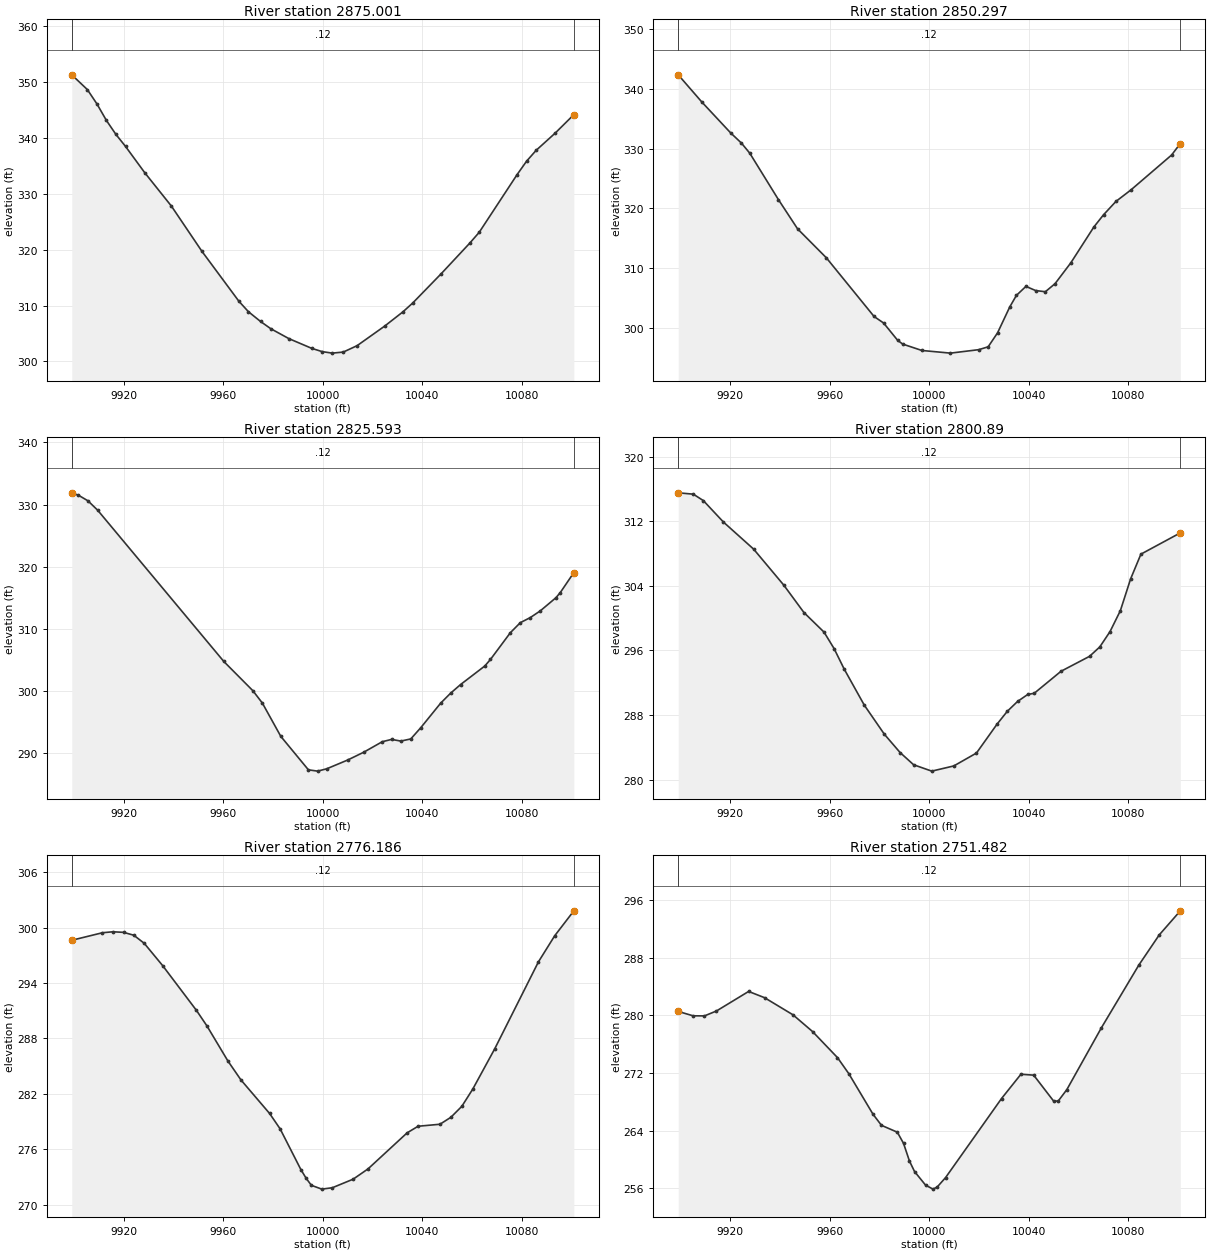
Type RM Length L Ch R = 1 ,2875.001,24.703700,24.703700,24.703700
XS GIS Cut Line= 6
1252192.12247484836552.9035372331252134.66675763836587.758922908
1252108.56754236836607.5785524541252106.97882673836608.793452713
1252079.97045553836628.5581220451252022.80203429836662.546696139
#Sta/Elev= 30
9899.027351.3006  9905.3348.65959909.137346.10239912.975343.12789916.812340.6197
9920.649338.48579928.324333.81459939.124327.79229951.348319.73039966.228310.7848
9970.107308.88869974.971307.14859979.091 305.8539986.382304.07789995.569302.3378
9999.691301.761110003.78301.485110008.24301.6737 10013.8302.820310024.91306.3304
10032.24308.877710036.19310.464710047.64315.705210059.09321.161710062.91323.1099
10078.17 333.45110081.99335.854510085.81337.783510093.44340.852310100.98344.1737
#Mann= 3 , 0 , 0
9899.027    0.12       09899.027    0.12       010100.98    0.12       0
#XS Ineff= 2 , 0
       09978.498                       0
Bank Sta=9899.027,10100.98
Exp/Cntr=0.3,0.1

Type RM Length L Ch R = 1 ,2850.297,24.703700,24.703700,24.703700
XS GIS Cut Line= 5
1252181.77745838836534.180545938 1252096.4896287 836586.37200145
1252094.84154488836587.5050591451252062.96789928836605.969052854
1252009.92669087836640.249761584
#Sta/Elev= 30
 9899.01342.31539908.556337.75029920.095  332.62 9924.44330.91639927.788329.2288
9939.327321.4706 9947.02316.59549958.559311.77719977.791301.96139981.637300.8665
9987.295297.9737 9989.33297.34849997.023296.284910008.52295.8412 10019.9296.4189
10023.69296.896510027.48299.236610032.37303.546310035.06305.486910038.88306.9854
10042.79306.2913 10046.7306.0937 10050.6307.440710056.96310.930110066.23316.9144
10070.14318.9628 10075.1321.176410081.14323.100110097.48328.920810100.99330.8368
#Mann= 3 , 0 , 0
 9899.01    0.12       0 9899.01    0.12       010100.99    0.12       0
#XS Ineff= 2 , 0
       0                10019.88       0
Bank Sta=9899.01,10100.99
Exp/Cntr=0.3,0.1

Type RM Length L Ch R = 1 ,2825.593,24.703700,24.703700,24.703700
XS GIS Cut Line= 6
1252169.27352418836513.189639656 1252106.3447544836553.713180912
1252084.07772262 836565.356620151252082.24358253836566.154072427
1252055.48288716836580.6093906791251998.53287296836620.507674598
#Sta/Elev= 30
9899.025 331.8799901.714 331.4929905.543330.59099909.446329.08029960.175 304.743
9971.881300.02989975.686298.0437 9983.09292.69519994.197 287.3069997.899287.0982
10001.54287.469810009.98288.883510016.45290.141510023.91291.832710027.64292.2014
10031.37291.934110035.37292.278110039.38 294.08310047.39298.037710051.39299.6398
 10055.4301.031510065.12304.009610067.42305.071310075.43309.378410079.43310.9879
10083.44311.808110087.45312.884110093.71314.988510095.46315.807710100.95319.0473
#Mann= 3 , 0 , 0
9899.025    0.12       09899.025    0.12       010100.95    0.12       0
#XS Ineff= 2 , 0
       0 9989.47        10020.23       0
Bank Sta=9899.025,10100.95
Exp/Cntr=0.3,0.1

Type RM Length L Ch R = 1 , 2800.89,24.703800,24.703800,24.703800
XS GIS Cut Line= 5
1252152.30310319836485.378399429 1252079.0802429836538.218537527
1252071.36979426836544.1065802441252069.79108986836545.334461521
1251990.45897973836606.192144659
#Sta/Elev= 30
9899.001315.51769905.061315.35299909.107314.55359917.199311.89389929.336308.5445
9941.474304.08399949.566300.69479957.658298.26819961.703296.22729965.749 293.699
9973.841289.23059981.933285.61919988.261283.35289993.704281.8396   10001281.0531
10009.87281.696110018.98283.292210027.25286.865310031.38288.460610035.52289.6832
10039.65290.556210042.21290.689910052.99 293.41910064.46295.2668 10068.6 296.435
10072.73298.341510076.87300.9226   10081304.863910085.14307.923910100.99310.5574
#Mann= 3 , 0 , 0
9899.001    0.12       09899.001    0.12       010100.99    0.12       0
#XS Ineff= 2 , 0
       09988.053                       0
Bank Sta=9899.001,10100.99
Exp/Cntr=0.3,0.1

Type RM Length L Ch R = 1 ,2776.186,24.703700,24.703700,24.703700
XS GIS Cut Line= 5
1252134.07020506836462.2722182651252055.99695413836524.751871532
1252054.43521655836526.0012616761252041.00487187 836536.72443974
1251979.29834232836591.948737712
#Sta/Elev= 30
9899.004 298.639 9911.36299.45639915.562299.55959919.816299.49849923.967299.1857
9928.169 298.3069935.568295.89179949.179291.03569953.381289.35749961.822285.5554
9967.073283.50119978.593279.86759982.826278.2019  9991.2273.77579993.327272.8332
9995.402272.08049999.604271.667510003.83271.8182 10012.2272.744310018.19273.8595
10033.92277.766510038.33278.481810047.13278.698810051.53279.453410055.94280.6452
10060.34282.512210069.15 286.86510086.76296.302510093.31 299.131   10101301.8303
#Mann= 3 , 0 , 0
9899.004    0.12       09899.004    0.12       0   10101    0.12       0
#XS Ineff= 2 , 0
       0                               0
Bank Sta=9899.004,10101
Exp/Cntr=0.3,0.1

Type RM Length L Ch R = 1 ,2751.482,24.703700,24.703700,24.703700
XS GIS Cut Line= 6
1252112.39844016836435.3044626051252062.76378297836481.210484806
1252040.99578319836505.1635803961252039.44355522836506.424765693
1252007.62140878836543.7040675611251971.52751302836579.687791053
#Sta/Elev= 30
9899.025280.5581 9904.99279.95079909.574279.93769914.406280.62079927.335283.3348
9933.734282.4704 9945.21 280.0839953.061277.75959963.086274.13859967.639271.9081
9977.396266.2607 9980.78264.73249987.152263.77659989.647  262.239992.031259.7727
 9994.08258.31159998.513256.4248 10001.5255.868210003.18256.157610006.55257.4676
10029.06268.453410036.87271.8302   10042271.704110050.01268.106610051.86268.1025
10055.33269.691610069.27278.305310084.29286.9954 10092.5 291.18910100.98294.5364
#Mann= 3 , 0 , 0
9899.025    0.12       09899.025    0.12       010100.98    0.12       0
#XS Ineff= 2 , 0
       0                               0
Bank Sta=9899.025,10100.98
Exp/Cntr=0.3,0.1

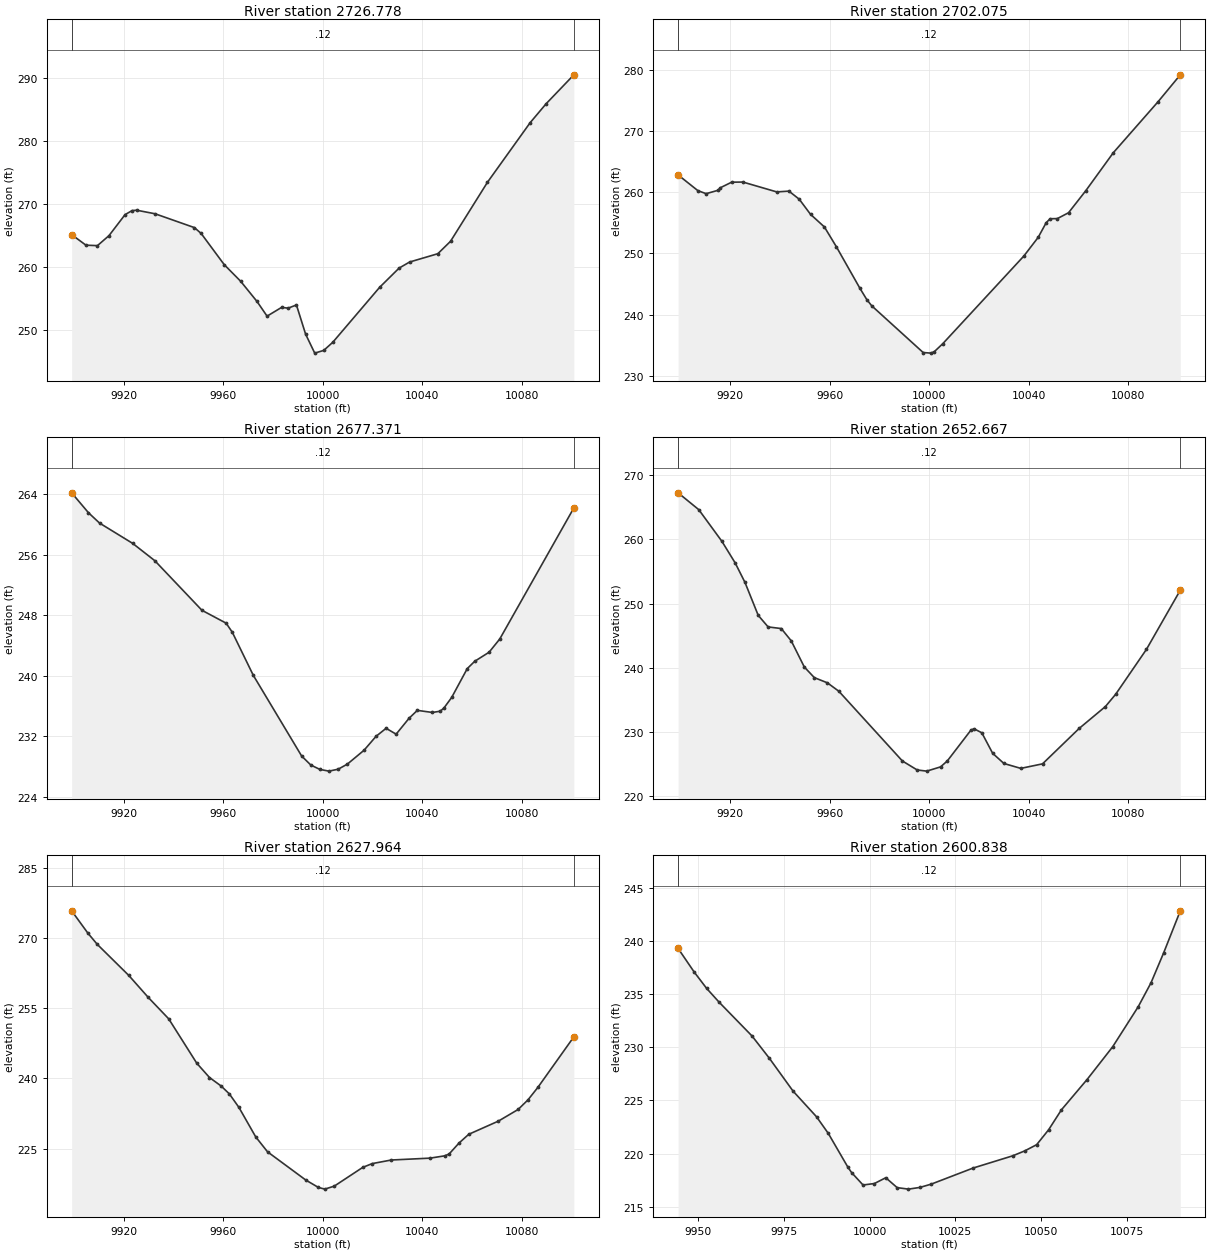
Type RM Length L Ch R = 1 ,2726.778,24.703700,24.703700,24.703700
XS GIS Cut Line= 6
1252083.81584063836418.7116694541252034.72098037 836467.94850663
1252024.47399682  836482.13440371252012.26008128836507.114034155
1252002.72269086836521.8134959671251955.94225003836573.201644009
#Sta/Elev= 30
9899.067265.15069904.815263.46879909.449263.39929914.082264.99029920.547268.3338
9923.348268.96789925.194269.03479932.614268.46739948.426266.26539951.147265.3297
9960.413260.37039967.012 257.732 9973.59254.51559977.637252.17819983.495 253.577
9986.097253.44979989.442 253.9599993.118249.32659996.795246.295510000.43246.7324
10004.06248.024410022.89256.765710030.71259.822210034.92260.787410046.29262.1133
 10051.4264.090110066.25 273.48510083.41 282.96110089.86285.986910100.97290.5741
#Mann= 3 , 0 , 0
9899.067    0.12       09899.067    0.12       010100.97    0.12       0
#XS Ineff= 2 , 0
       0                               0
Bank Sta=9899.067,10100.97
Exp/Cntr=0.3,0.1

Type RM Length L Ch R = 1 ,2702.075,24.703700,24.703700,24.703700
XS GIS Cut Line= 5
1252071.12658554836411.7311949231251998.70642204836480.687704054
1251997.24734767836482.0555863581251979.11452698836499.333405325
1251927.82965908836553.982326094
#Sta/Elev= 30
9899.002262.82919906.953 260.262 9910.27259.76739915.028260.31699916.014260.7417
9920.544261.64799925.074261.66499938.665 260.0569943.574260.18329947.725258.8607
9952.255256.39319957.848254.32419962.605251.12669972.121244.30569974.906242.4454
9976.879241.43829997.557233.805110000.68233.705410002.07233.952210005.44235.2426
10038.05249.569410043.83252.629610047.05255.024910048.63255.671210051.54255.6941
10056.04256.651910063.01260.271810074.04266.459310092.04274.792910100.99279.1923
#Mann= 3 , 0 , 0
9899.002    0.12       09899.002    0.12       010100.99    0.12       0
#XS Ineff= 2 , 0
       0                10015.47       0
Bank Sta=9899.002,10100.99
Exp/Cntr=0.3,0.1

Type RM Length L Ch R = 1 ,2677.371,24.703800,24.703800,24.703800
XS GIS Cut Line= 6
1252063.79136929836397.2578535831252012.49558262836444.208525256
1251970.85029785836467.9581686491251956.36241069836478.385800982
1251937.95297829 836496.493524561251911.69151829836527.537246305
#Sta/Elev= 30
9899.054264.17999905.812261.5493 9910.26260.18379923.603257.49429932.498255.2049
9951.436248.65299961.155246.95239963.631245.75639972.085240.05429991.517229.3911
9995.195228.20169998.874227.616110002.52227.393310006.22227.648510009.92228.3246
10016.62 230.15910021.43 231.99210025.47233.052810029.51232.279410034.71234.3822
10038.03235.424810044.07235.149110047.24235.313910048.75 235.74810051.84237.1339
 10058.1240.946310061.12 241.91710066.88243.111210071.17244.858510100.95 262.183
#Mann= 3 , 0 , 0
9899.054    0.12       09899.054    0.12       010100.95    0.12       0
#XS Ineff= 2 , 0
       0                 10014.4       0
Bank Sta=9899.054,10100.95
Exp/Cntr=0.3,0.1

Type RM Length L Ch R = 1 ,2652.667,24.703700,24.703700,24.703700
XS GIS Cut Line= 6
1252048.26772824836370.4381949721251998.72268493836420.143493315
1251963.45166245836445.5402162961251951.44980207836456.013917049
1251934.14494517836475.7090867681251906.20061875836512.357312423
#Sta/Elev= 30
9899.032267.27579907.341 264.6489916.635259.70859921.983256.3298 9925.93253.2848
9931.248248.14889935.224246.34529940.512246.09199944.519244.17489949.777240.0917
9953.814238.42969959.042237.62479963.674236.30289989.221225.42019995.171224.0179
    9999223.839110004.56224.501310007.25225.416110016.81230.255310018.04230.4462
10021.16229.821210025.52226.618510030.04225.032110036.83224.268310045.57224.9746
10060.31230.505810070.84233.914910074.96235.826110087.36 242.84710100.97252.0851
#Mann= 3 , 0 , 0
9899.032    0.12       09899.032    0.12       010100.97    0.12       0
#XS Ineff= 2 , 0
       0                10012.13       0
Bank Sta=9899.032,10100.97
Exp/Cntr=0.3,0.1

Type RM Length L Ch R = 1 ,2627.964,27.126100,27.126100,27.126100
XS GIS Cut Line= 6
1252013.52575773836339.0617759081251977.47400231836387.153980333
 1251956.7096256836421.1749322911251955.75192139836422.930723466
1251935.06480384836457.7703532261251901.61737669836506.936273039
#Sta/Elev= 30
9899.038275.76749905.593 270.9839909.363268.59789922.003261.98279929.865257.2709
9938.066252.71149949.351243.23719954.467240.18419959.143238.37179962.447236.6889
9966.291 233.816 9973.06227.50669977.821224.31599993.196218.2932 9998.25216.7221
10000.83216.357310004.64216.994910016.09220.999210019.91221.808810027.54222.5703
10043.17222.973810049.01223.459710050.79223.837210054.84226.212610058.72 228.062
10070.63230.873610078.56233.357710082.53 235.408 10086.5238.064510100.98248.8673
#Mann= 3 , 0 , 0
9899.038    0.12       09899.038    0.12       010100.98    0.12       0
#XS Ineff= 2 , 0
       0                10018.95       0
Bank Sta=9899.038,10100.98
Exp/Cntr=0.3,0.1

Type RM Length L Ch R = 1 ,2600.838,21.680100,21.680100,21.680100
XS GIS Cut Line= 6
1251950.16891864836362.8167793751251937.70110402836388.333179057
1251931.56350669836408.6193546651251925.98753995836444.691469625
1251918.75205392836465.0356813821251900.24557856836499.204472572
#Sta/Elev= 30
9944.131239.29989948.796 237.0919952.448235.54429956.099234.24169965.708231.0591
9970.705228.99039977.673225.87669984.528223.45859987.956221.89589993.725218.6905
9994.777 218.2019998.095  217.0410001.41217.178610004.73217.724210008.05216.7925
10011.35216.651810014.68216.8119   10018217.121710030.23218.6374 10041.8219.7897
10045.28220.249910048.76220.833310052.27222.2456   10056224.118910063.47226.9649
10070.93230.040510078.39233.811510082.12236.059610085.85238.907210090.68242.8401
#Mann= 3 , 0 , 0
9944.131    0.12       09944.131    0.12       010090.68    0.12       0
#XS Ineff= 2 , 0
       09990.241        10021.46       0
Bank Sta=9944.131,10090.68
Exp/Cntr=0.3,0.1

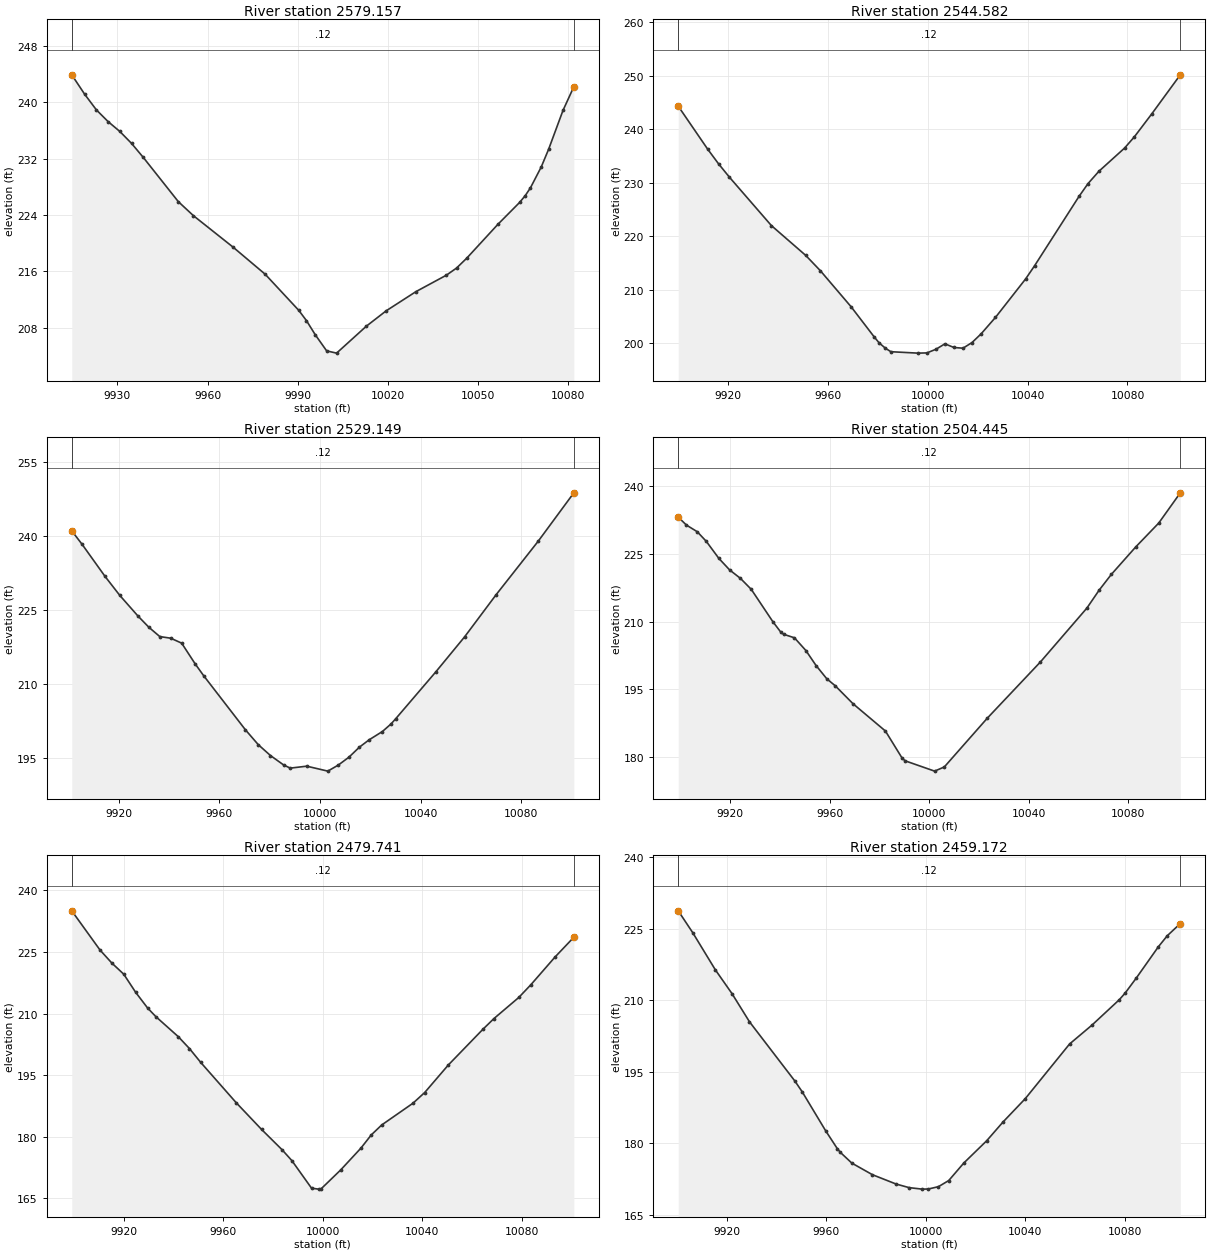
Type RM Length L Ch R = 1 ,2579.157,34.575600,34.575600,34.575600
XS GIS Cut Line= 6
1251945.64439297836337.151108325 1251915.9849332 836388.55258511
1251909.53476351836409.1607006641251905.35211831836445.412480533
1251899.86455089836465.8812138591251887.97941574836491.671979904
#Sta/Elev= 30
9914.795243.91319919.085241.15539922.984 238.9349926.883237.26729930.782  235.87
9934.681 234.174 9938.58232.18489950.263225.8895  9955.3223.89179968.517219.4135
9979.164215.5777 9990.36210.43919992.916208.98149995.831206.98169999.641204.6794
10002.95204.360410012.87208.195210019.46 210.37610029.37213.103310039.47215.4326
10042.87216.448510046.26  217.8510056.64222.665910063.86225.774210065.71226.7254
10067.48227.855910071.09230.838810073.55233.362310078.31238.856910081.92242.2229
#Mann= 3 , 0 , 0
9914.795    0.12       09914.795    0.12       010081.92    0.12       0
#XS Ineff= 2 , 0
       09990.221        10020.06       0
Bank Sta=9914.795,10081.92
Exp/Cntr=0.3,0.1

Type RM Length L Ch R = 1 ,2544.582,15.433100,15.433100,15.433100
XS GIS Cut Line= 6
1251942.34627301  836328.63155591251908.05807859836367.694055915
1251879.41224524836397.2079447951251867.69349524836422.381555915
1251849.03030077836465.7843336761251833.41723713836494.863358289
#Sta/Elev= 30
9900.029 244.2919911.804236.2774 9916.17233.53239920.535231.02939937.344221.9934
9951.093216.42579956.961 213.5669969.339206.79659978.483 201.2279980.514200.0815
9983.055199.07269985.224198.43219996.013 198.1689999.632198.208510003.25198.8837
10006.87199.905510010.49199.219410014.11199.090110017.73200.145610021.34201.7553
10027.12204.8409 10039.2212.027310042.77214.472510060.62227.4621 10064.2229.8336
10068.57232.140510078.86 236.47610082.73 238.54810089.81242.898910101.17250.1473
#Mann= 3 , 0 , 0
9900.029    0.12       09900.029    0.12       010101.17    0.12       0
#XS Ineff= 2 , 0
       09986.114        10017.56       0
Bank Sta=9900.029,10101.17
Exp/Cntr=0.3,0.1

Type RM Length L Ch R = 1 ,2529.149,24.703700,24.703700,24.703700
XS GIS Cut Line= 6
1251937.57196745836328.1975281241251876.80807859836381.148917034
1251871.02088258 836385.620841221251864.85521162836393.293216929
1251863.63231671 836394.875786961251801.54608083836473.265328184
#Sta/Elev= 30
9901.245241.00199905.388238.25059914.508231.75399920.369227.91059927.563223.7499
9931.915221.46349936.267219.57499940.619219.2446 9944.97218.24029950.332214.0456
9953.674211.67359970.307200.69199975.433197.66949980.295 195.4599985.546193.5438
9988.174192.90629994.742193.301410003.12192.2972 10007.3193.530810011.49 195.112
10015.67197.149710019.55 198.64510024.84200.329810028.23201.844610030.12202.9132
10045.97212.351110057.53219.512210070.08228.065410086.82 238.907   10101248.7147
#Mann= 3 , 0 , 0
9901.245    0.12       09901.245    0.12       0   10101    0.12       0
#XS Ineff= 2 , 0
       09986.288        10017.89       0
Bank Sta=9901.245,10101
Exp/Cntr=0.3,0.1

Type RM Length L Ch R = 1 ,2504.445,24.703700,24.703700,24.703700
XS GIS Cut Line= 6
1251918.57061481836305.4576459841251877.19180215836353.130528182
 1251861.1925802836367.0458957951251837.68931155836382.532515156
1251822.48581997836394.7925803281251774.56835028836445.642359615
#Sta/Elev= 30
9899.055233.1894 9902.36231.42689906.704229.95279910.347227.81619915.393224.0372
9919.737221.47489924.081   219.69928.426217.17079937.114209.99279940.378207.6207
9941.459207.19899945.803206.41729950.388203.60259954.492200.26419958.836197.3067
9962.181195.78699969.329191.80289982.373 185.7429989.169179.65719990.388179.1129
10002.15176.843110006.07177.772210023.39188.614410044.74201.0793 10063.4213.0144
10068.32216.986610073.24220.492210083.08 226.60310092.31231.887710100.97238.5844
#Mann= 3 , 0 , 0
9899.055    0.12       09899.055    0.12       010100.97    0.12       0
#XS Ineff= 2 , 0
       09984.226                       0
Bank Sta=9899.055,10100.97
Exp/Cntr=0.3,0.1

Type RM Length L Ch R = 1 ,2479.741,20.568900,20.568900,20.568900
XS GIS Cut Line= 6
1251909.12332233836286.6505496641251868.33026189836329.892837427
1251851.78041444836343.791107622 1251825.4128637 836361.14136881
1251810.01377669836373.5150335561251761.67343476836423.478332373
#Sta/Elev= 30
9899.045235.02949910.407225.48099915.188 222.2939919.969219.5863 9924.75215.1755
9929.532211.37039932.841209.27069941.862204.39359946.372201.48839950.882198.1306
9965.189188.28889975.393181.77929983.647176.82879987.591174.1737 9995.48167.4756
9998.288167.24579999.412167.363510007.21171.9235 10015.3177.2037 10019.5180.4452
10023.71182.876610036.25 188.158   10041 190.77610050.49197.477310064.38206.1645
10068.84208.786710078.84213.929510083.69217.024510093.39223.761110100.98228.5998
#Mann= 3 , 0 , 0
9899.045    0.12       09899.045    0.12       010100.98    0.12       0
#XS Ineff= 2 , 0
       09984.306                       0
Bank Sta=9899.045,10100.98
Exp/Cntr=0.3,0.1

Type RM Length L Ch R = 1 ,2459.172,28.838600,28.838600,28.838600
XS GIS Cut Line= 6
1251890.13957732836267.7051952781251829.47973812836330.175551462
1251821.43110963836340.2552896511251820.31216392836341.912986999
 1251812.4182275836352.1182943611251753.43071791 836416.16594972
#Sta/Elev= 30
9900.448228.78849906.245 224.2299915.391216.38659922.066211.4102 9929.11205.4847
9947.402193.02179950.323190.77559959.742182.60379964.452 178.8349965.695178.0506
9970.268175.81389978.581173.36969988.055171.42119993.313170.65969998.571170.3463
10001.03170.370610005.11170.861810009.26 172.15110015.32175.833310024.53180.5124
10031.11184.456410040.03 189.34210057.87200.832810066.79204.7544 10077.8210.0924
10080.17211.492510084.63214.627210093.55221.224410097.17223.5654 10102.4226.1169
#Mann= 3 , 0 , 0
9900.448    0.12       09900.448    0.12       0 10102.4    0.12       0
#XS Ineff= 2 , 0
       09989.251                       0
Bank Sta=9900.448,10102.4
Exp/Cntr=0.3,0.1

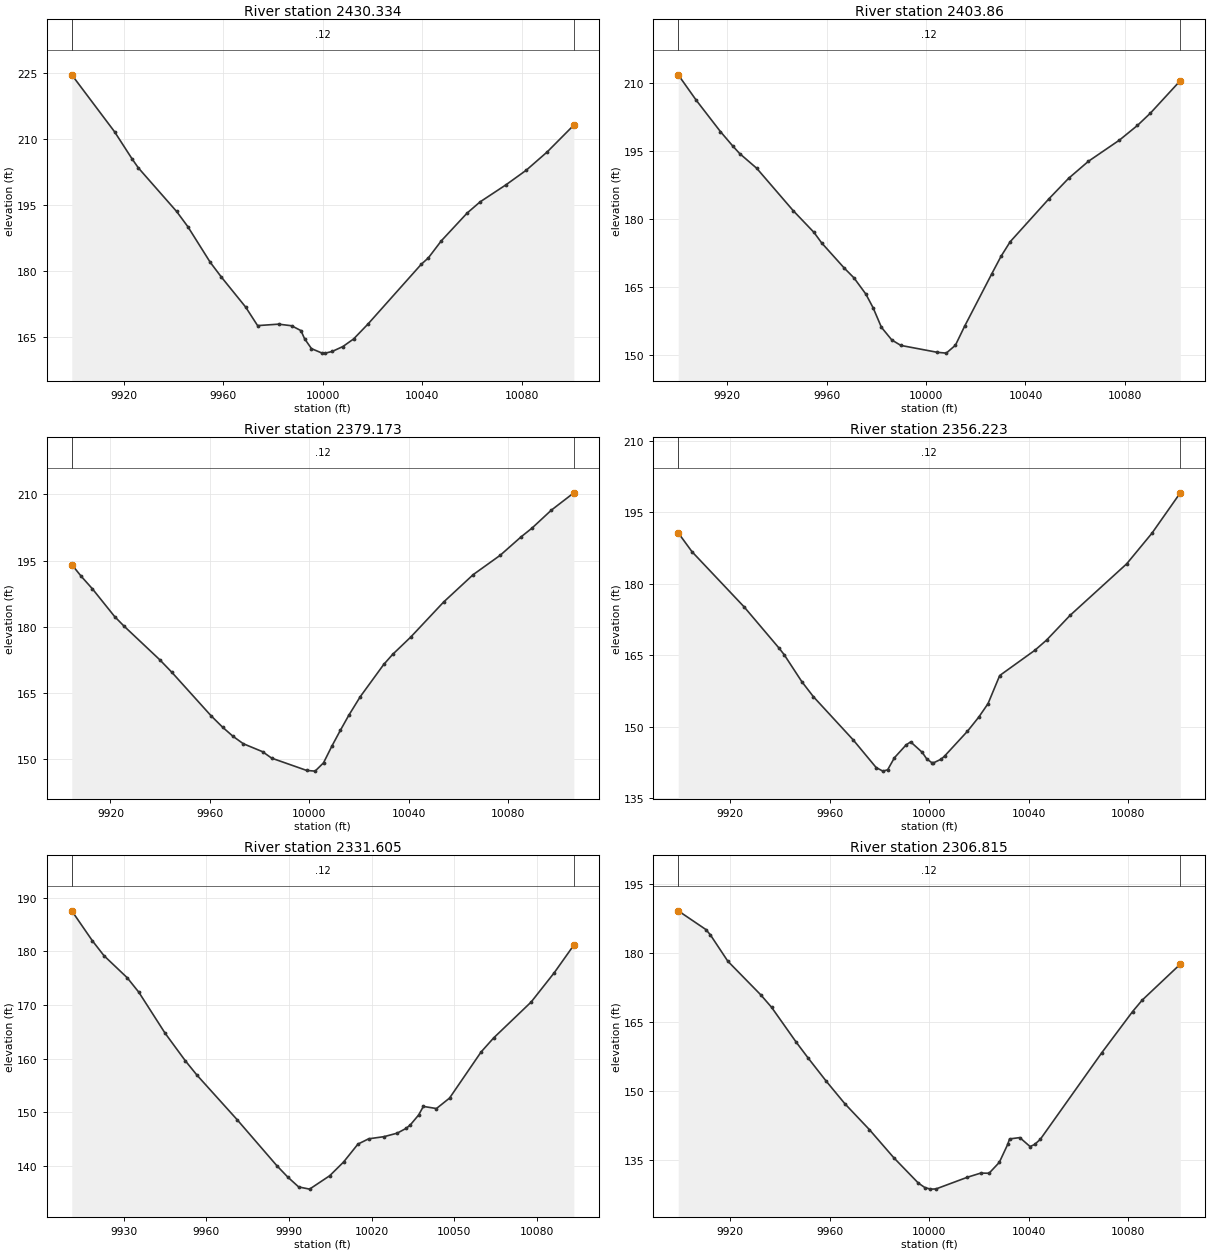
Type RM Length L Ch R = 1 ,2430.334,26.474000,26.474000,26.474000
XS GIS Cut Line= 6
1251873.71703323 836247.678515651251819.50267691836305.456396741
1251803.40930923836318.5189030731251801.73785857836319.617198444
1251788.65442808836330.6895613641251736.53894969836395.024519551
#Sta/Elev= 30
9899.042 224.5099916.229211.5949 9923.21205.48999925.819203.37089941.206193.4725
9945.705190.02979954.703181.94319959.202178.57129968.971  171.759973.766167.5471
9982.235167.87879987.441167.51429991.203166.40729992.647 164.5789995.429162.3174
9999.608161.3239   10001161.297710003.77161.681210008.07162.797810012.37164.5168
10018.14167.896710039.55181.464310042.42182.926310047.63186.798110058.05193.1294
10063.26195.661910073.69199.548310081.77202.833510090.21206.995410100.93213.0903
#Mann= 3 , 0 , 0
9899.042    0.12       09899.042    0.12       010100.93    0.12       0
#XS Ineff= 2 , 0
       0 9990.07                       0
Bank Sta=9899.042,10100.93
Exp/Cntr=0.3,0.1

Type RM Length L Ch R = 1 , 2403.86,24.687100,24.687100,24.687100
XS GIS Cut Line= 6
1251840.60559652836224.1226116821251799.38743809836272.179676583
1251789.16839076836288.8220758361251764.53310625836338.579606084
1251747.23175456836363.6239502461251726.44452257836389.339025435
#Sta/Elev= 30
9900.358 211.7039907.609206.09649917.326199.20059922.185196.08629925.052194.3613
9931.903191.12549946.583181.78239954.946176.98929958.044174.66829967.191169.0898
9971.041166.96469975.806163.40259978.741160.36399982.076156.07519986.265153.2785
9989.902152.084710004.53150.570710008.15150.388910011.82152.121310015.49156.2723
10026.51167.928110030.19171.735410033.86174.934210049.39184.361810057.37 188.912
10065.34192.664110077.78 197.31610085.03200.552210090.25203.264410102.27210.4177
#Mann= 3 , 0 , 0
9900.358    0.12       09900.358    0.12       010102.27    0.12       0
#XS Ineff= 2 , 0
       09988.536                       0
Bank Sta=9900.358,10102.27
Exp/Cntr=0.3,0.1

Type RM Length L Ch R = 1 ,2379.173,22.950000,22.950000,22.950000
XS GIS Cut Line= 6
1251813.88540361836223.1478104351251766.64246134836277.777423846
1251760.00157836836290.9310275531251745.28101768836336.470771335
1251728.42435338836361.9167916681251705.26360119836389.864347987
#Sta/Elev= 30
9904.442194.07479908.244191.41889912.724188.58859921.683182.28319925.394180.1553
 9939.85172.47189944.669169.65459960.443159.78699965.077157.19879969.236155.1405
9973.395153.44759981.134151.6428 9984.81150.17519998.884147.386410002.27147.2303
10005.66149.112710009.04152.929510012.42156.4779 10015.8159.879510020.42164.1095
10029.85171.417610033.42173.693210040.69177.619910053.96185.591410065.84191.8019
10076.68196.181710085.13200.3855 10089.4202.311410097.25206.4231 10106.3210.3529
#Mann= 3 , 0 , 0
9904.442    0.12       09904.442    0.12       0 10106.3    0.12       0
#XS Ineff= 2 , 0
       09985.577                       0
Bank Sta=9904.442,10106.3
Exp/Cntr=0.3,0.1

Type RM Length L Ch R = 1 ,2356.223,24.617800,24.617800,24.617800
XS GIS Cut Line= 4
1251808.42775078836218.708575043 1251737.9719761 836289.56693705
1251736.66211507836291.0783152561251666.98780039836362.783465925
#Sta/Elev= 30
9899.075 190.6579904.636186.69299925.526175.16699939.485166.57649941.649165.1453
9948.791159.45179953.444156.30439969.409147.27149978.662141.46049981.362140.7082
9983.289140.98439986.016143.51589990.669146.18339992.542146.83659997.169144.6625
    9999143.2711   10001142.499110001.66142.429110004.81143.216310006.23  143.89
10015.38149.067210019.95152.044410023.65154.853810028.35160.748310042.48166.0388
10047.19168.1767 10056.6173.337610079.42184.169210089.56190.575410100.98  199.05
#Mann= 3 , 0 , 0
9899.075    0.12       09899.075    0.12       010100.98    0.12       0
#XS Ineff= 2 , 0
       09975.998        10009.95       0
Bank Sta=9899.075,10100.98
Exp/Cntr=0.3,0.1

Type RM Length L Ch R = 1 ,2331.605,24.789700,24.789700,24.789700
XS GIS Cut Line= 4
1251802.15530077836214.4822503631251750.81443909836255.974176913
1251727.96593156836271.4872739611251666.73863411836335.576000348
#Sta/Elev= 30
9911.127187.56179918.604181.98029922.823179.19549931.259175.08059935.477172.3748
9945.002 164.7429952.351159.59599956.569 156.923  9971.1148.6414 9985.56140.0391
9989.526 137.9149993.492136.06689997.457135.657210004.76138.154510009.81 140.719
10015.01144.052410018.89145.040710024.51145.445710029.26146.0959 10032.5146.9881
10034.01147.625410037.04149.482210038.76151.083410043.51150.688210048.26152.6343
10059.73161.246210064.26163.849910077.87 170.54210086.25175.998310093.39181.1718
#Mann= 3 , 0 , 0
9911.127    0.12       09911.127    0.12       010093.39    0.12       0
#XS Ineff= 2 , 0
       0                10015.27       0
Bank Sta=9911.127,10093.39
Exp/Cntr=0.3,0.1

Type RM Length L Ch R = 1 ,2306.815,24.703700,24.703700,24.703700
XS GIS Cut Line= 5
1251794.80868808836181.2127799451251720.30451101836247.883829141
1251718.84811107836249.2545585841251710.18809953 836257.17626324
1251640.01115325836310.685481303
#Sta/Elev= 30
 9899.02189.07139910.174184.99189911.963183.83449918.979178.11449932.187170.8268
9936.562168.10539946.402160.57879951.322157.04439958.603152.01049966.082147.1225
9975.922141.51189985.762135.38459995.601129.89739998.227128.920810000.48128.5778
10002.69128.616710015.32131.157310020.73 132.06710024.05132.027410028.17134.3892
10031.55138.2986 10032.3139.488810036.42139.779610040.55137.832410042.37138.2797
10044.67139.407510069.43158.248410081.81167.188110085.66169.663910100.99177.4806
#Mann= 3 , 0 , 0
 9899.02    0.12       0 9899.02    0.12       010100.99    0.12       0
#XS Ineff= 2 , 0
       0                10019.13       0
Bank Sta=9899.02,10100.99
Exp/Cntr=0.3,0.1