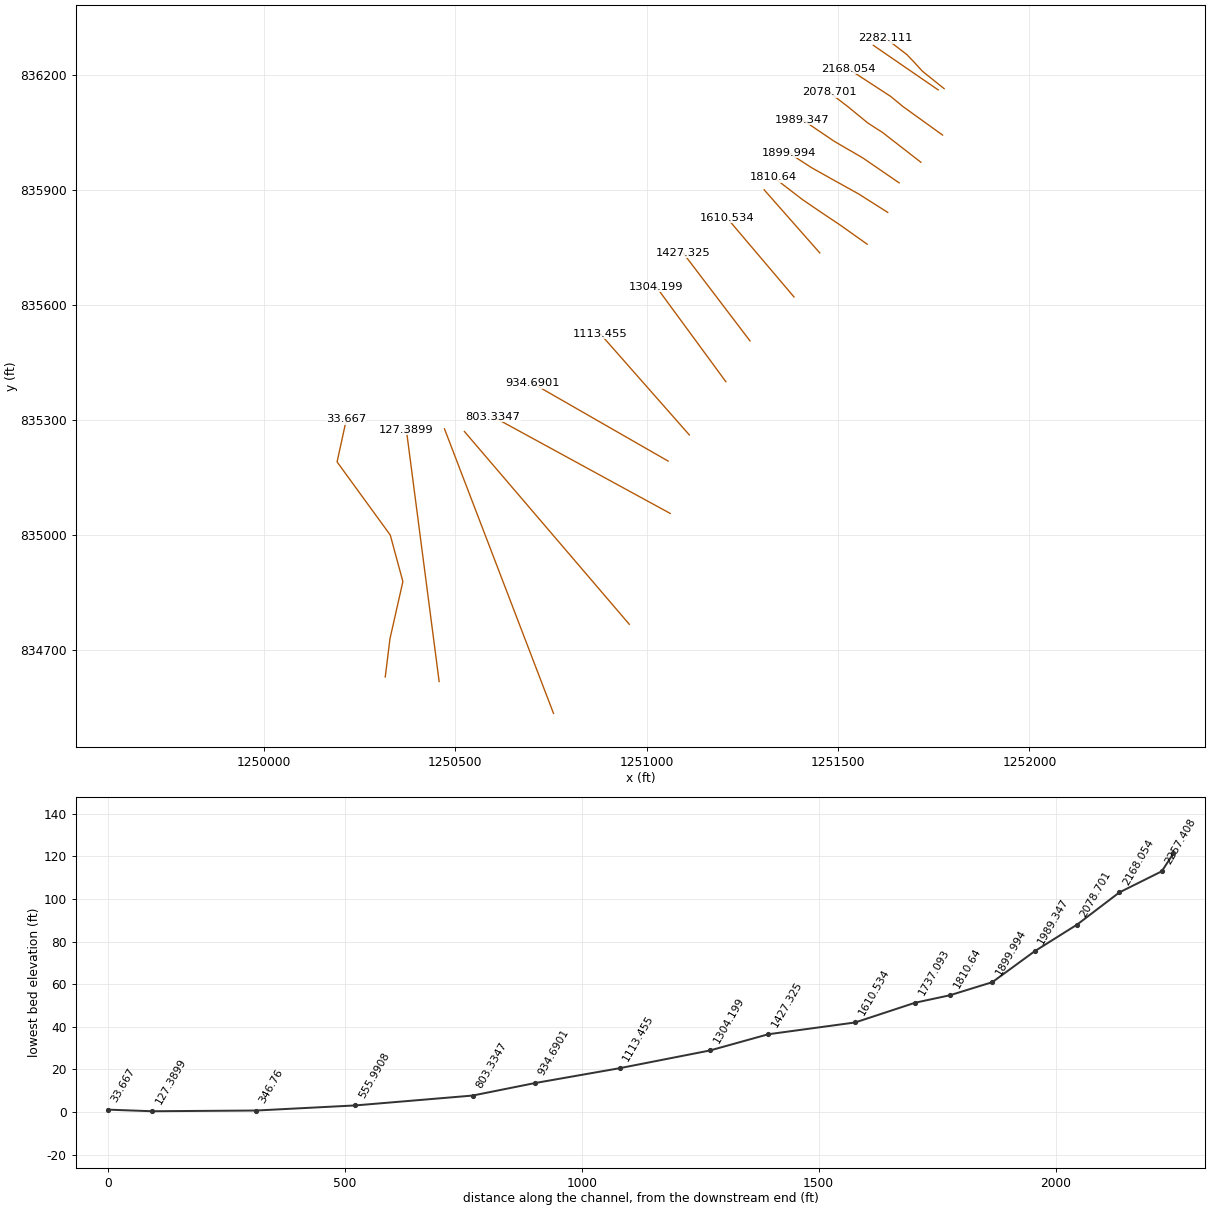
HEC-RAS study 72_ras.prj: 72

--- 72_ras.g01 (geometry) --- (continued)

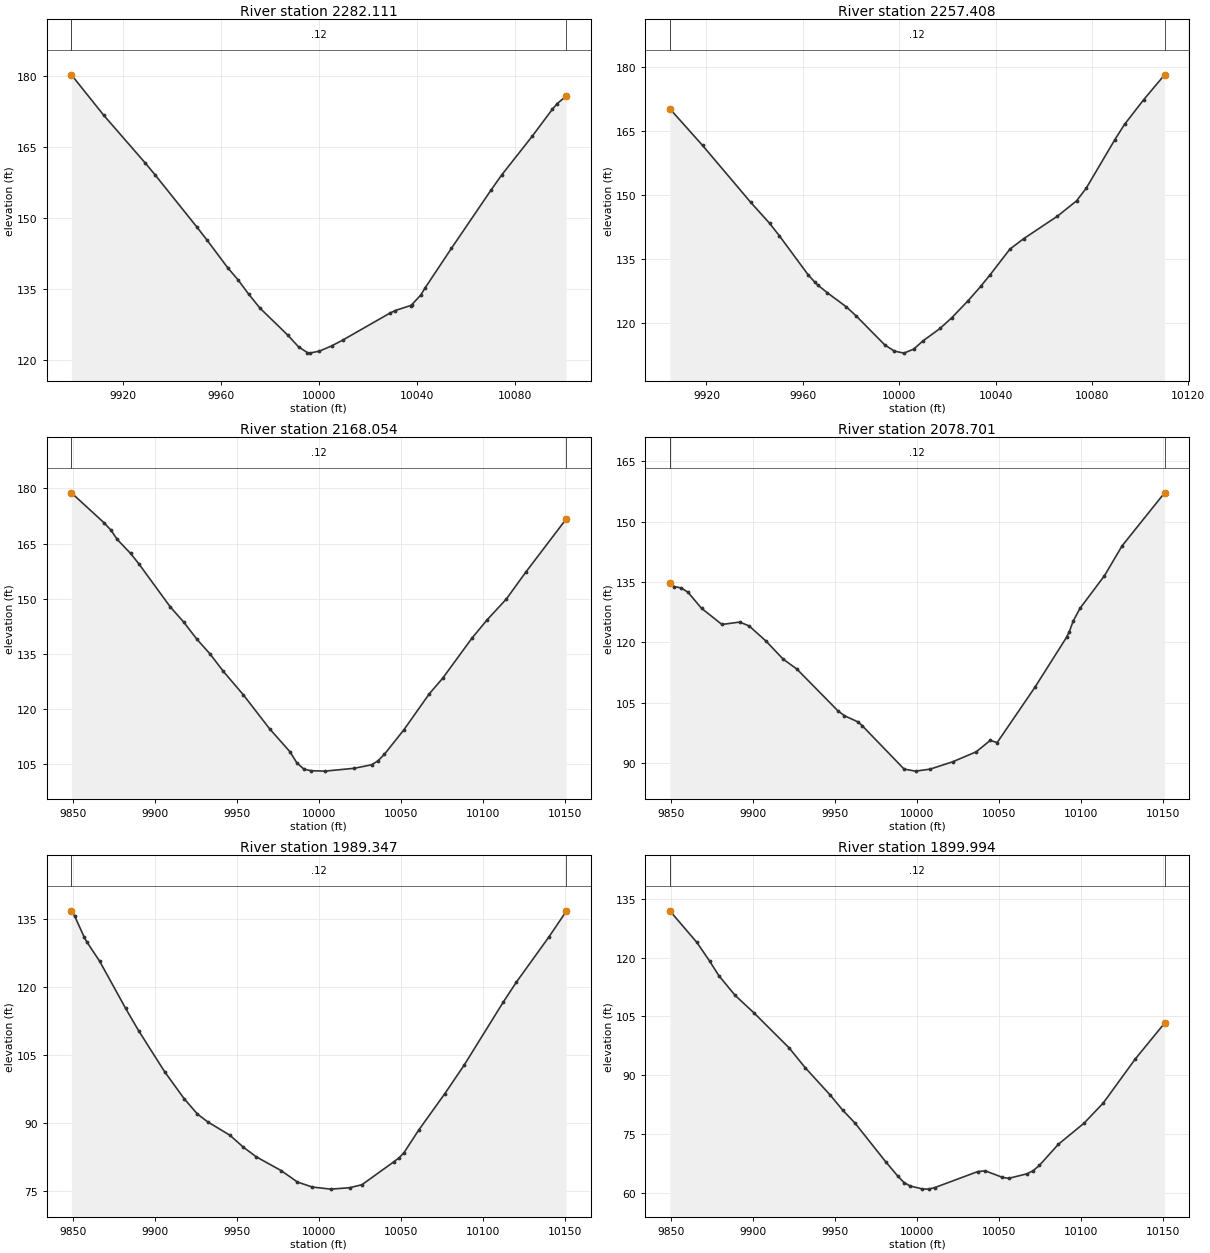
Type RM Length L Ch R = 1 ,2282.111,24.703700,24.703700,24.703700
XS GIS Cut Line= 6
1251777.16223361836165.6483450171251720.75233826836210.881323621
1251702.01913347836231.2175888341251700.72220056836232.740075298
1251679.94031984836254.6166933591251624.54973044836297.036590467
#Sta/Elev= 30
9899.045180.23759912.311171.64329929.133 161.6239933.338158.99239950.159 148.103
9954.365145.30769962.776139.47549966.981136.9236 9971.35133.88159976.004 130.894
9987.354  125.189991.814122.66929995.373121.49729996.275121.381810000.27121.8136
10005.19122.896510009.71124.124610028.89129.803110031.17130.388110037.46131.4505
10037.96 131.63610041.59133.653510043.35135.153710054.14143.561510070.33155.9013
10074.65159.076710087.05167.225410095.31172.965110097.31 174.16910100.94175.7198
#Mann= 3 , 0 , 0
9899.045    0.12       09899.045    0.12       010100.94    0.12       0
#XS Ineff= 2 , 0
       0                10021.56       0
Bank Sta=9899.045,10100.94
Exp/Cntr=0.3,0.1

Type RM Length L Ch R = 1 ,2257.408,89.353500,89.353500,89.353500
XS GIS Cut Line= 2
1251761.61457449836162.3848111331251592.34374118836278.704255566
#Sta/Elev= 30
 9904.78170.17299918.377161.58629938.281 148.3239946.243143.32639950.223140.4707
9962.166131.33729964.849129.66739966.147128.94279970.127127.12459978.089123.7913
9982.228121.63549994.012114.89839997.993113.458510001.97112.977510005.95113.9013
10009.94115.867510016.99118.766310021.88121.300310028.57125.227410033.82128.5927
 10037.8131.364310045.95137.320610051.74139.795510065.67145.026810073.63148.6219
10077.61151.567210089.55162.974110093.53166.507110101.49172.299310110.16178.1133
#Mann= 3 , 0 , 0
 9904.78    0.12       0 9904.78    0.12       010110.16    0.12       0
#XS Ineff= 2 , 0
       0                10019.62       0
Bank Sta=9904.78,10110.16
Exp/Cntr=0.3,0.1

Type RM Length L Ch R = 1 ,2168.054,89.353600,89.353600,89.353600
XS GIS Cut Line= 6
1251773.15103369836044.4377531171251669.94595699836118.644980905
1251652.30121689836133.183703205 1251650.8293549836134.537816309
1251637.49066322836145.3545999151251526.29225717836217.936047116
#Sta/Elev= 30
9849.023178.79319868.953170.64579872.994168.71479877.035166.09639885.117162.3113
9890.159159.50019909.362147.76389917.444143.69119925.525139.01519933.607134.9757
9941.689130.25849953.812123.92199969.975114.60689982.408108.35559986.659105.2915
 9990.91103.63489995.161103.207810003.74103.084310021.54 103.85310032.21104.8083
10036.13105.894110040.05 107.684 10051.8114.252110067.47124.147210075.56128.3297
10093.56139.311710102.73144.244310114.49 149.92410126.24157.170710150.96171.6578
#Mann= 3 , 0 , 0
9849.023    0.12       09849.023    0.12       010150.96    0.12       0
#XS Ineff= 2 , 0
       0                10023.57       0
Bank Sta=9849.023,10150.96
Exp/Cntr=0.3,0.1

Type RM Length L Ch R = 1 ,2078.701,89.353500,89.353500,89.353500
XS GIS Cut Line= 6
1251716.46914392835973.383373433 1251616.0904879836051.376405858
1251595.13460204836064.7260375131251577.73496146836076.070898995
1251527.04061535   836117.6302711251476.58407798836156.422496656
#Sta/Elev= 30
 9849.03134.63699851.753133.81919855.907133.49699860.062 132.4479868.372128.4361
9880.836124.41099891.685125.00679897.455124.03439907.727120.27979918.229115.7757
9926.539113.33239951.467103.00759955.622101.71499963.931100.17459966.54799.19986
9992.00888.45392    9999 87.946410007.8288.4383610021.7790.2852710036.0692.76222
10044.5595.5916610048.7995.0411210071.85108.799310091.12121.208810092.76122.5475
10095.26125.3274 10099.4128.448110114.29136.542610125.06143.965510150.97157.1377
#Mann= 3 , 0 , 0
 9849.03    0.12       0 9849.03    0.12       010150.97    0.12       0
#XS Ineff= 2 , 0
       0                10029.69       0
Bank Sta=9849.03,10150.97
Exp/Cntr=0.3,0.1

Type RM Length L Ch R = 1 ,1989.347,89.353500,89.353500,89.353500
XS GIS Cut Line= 6
1251659.61638062835919.6319261161251566.32801275835983.671586421
1251534.62488986836002.4010346661251532.82184377836003.266496857
1251490.71532987836027.7858634441251406.90240399836084.581770446
#Sta/Elev= 30
9849.024136.89649851.114 135.6599856.911131.02559858.283130.11269866.242125.7891
 9882.16115.33879890.119110.39369906.036101.32399917.97595.368499925.934 92.0456
9932.27290.304799945.83187.34456 9953.7984.784429961.749 82.6196 9977.0179.56878
9986.95577.039429996.06375.9295310007.3875.4707510018.7775.7783910026.36 76.4497
10045.7881.4973910049.1482.4307910052.0483.53721   1006188.5182610076.8696.51367
10088.74 102.85810112.52116.715910120.45121.092610140.27131.046810150.97136.7628
#Mann= 3 , 0 , 0
9849.024    0.12       09849.024    0.12       010150.97    0.12       0
#XS Ineff= 2 , 0
       0                10031.67       0
Bank Sta=9849.024,10150.97
Exp/Cntr=0.3,0.1

Type RM Length L Ch R = 1 ,1899.994,89.353600,89.353600,89.353600
XS GIS Cut Line= 6
1251629.87104846835842.4701796561251553.27777215835891.031186422
1251501.46124388835919.8292650361251499.64887762 835920.67503602
1251430.79859812 835959.331810081251371.20856819835997.953287395
#Sta/Elev= 30
9849.028131.92539865.578123.84969873.348 119.0919878.926115.40299888.886110.3651
 9900.54 105.8399921.81696.981069931.61791.936859946.90584.946389954.41281.14982
9961.91977.856089980.68667.972389988.19364.250279991.94762.63639  9995.761.74983
10003.1461.00087 10006.960.9497710010.6661.33336   1003765.4321210041.4965.61819
10052.0563.9499810055.82 63.7001 10067.164.8664510070.8765.6915610074.63 67.0386
10086.1572.3914510101.7977.7561210113.5282.9007210133.0694.1309410150.97103.2828
#Mann= 3 , 0 , 0
9849.028    0.12       09849.028    0.12       010150.97    0.12       0
#XS Ineff= 2 , 0
       0                               0
Bank Sta=9849.028,10150.97
Exp/Cntr=0.3,0.1

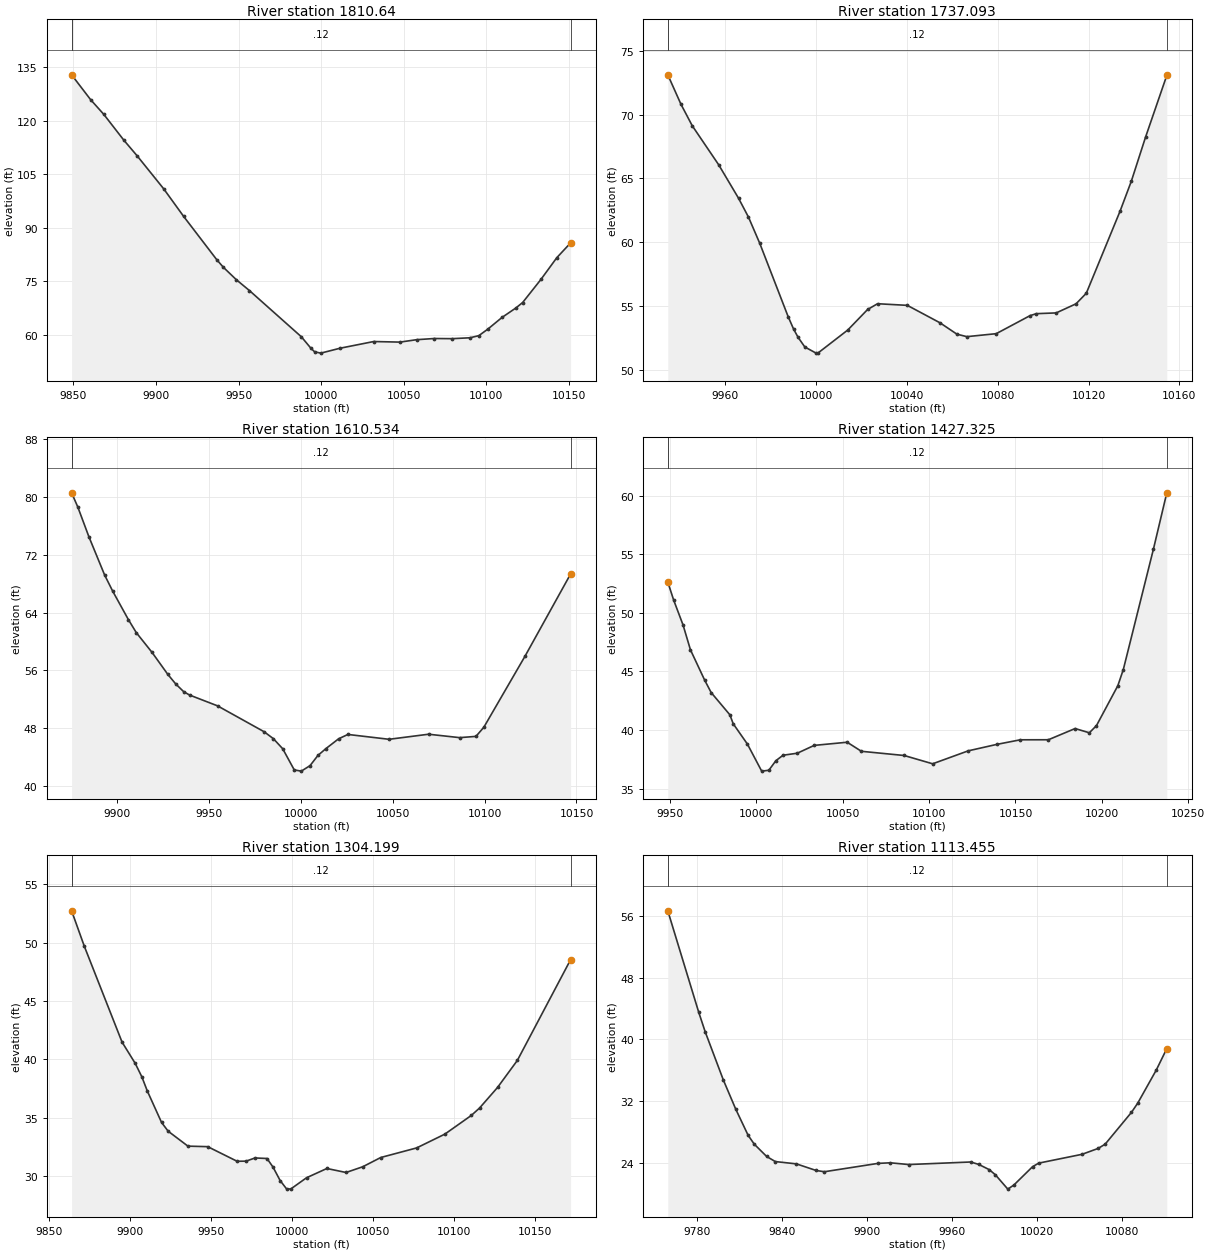
Type RM Length L Ch R = 1 , 1810.64,73.546600,73.546600,73.546600
XS GIS Cut Line= 6
1251576.01702541835759.4786955111251506.64176661835808.779165812
1251452.73831696835844.9022651571251451.07421641  835846.0116656
1251406.52251972835876.4160504141251330.43962139835935.035600691
#Sta/Elev= 30
9849.003132.90049860.456  125.969868.506121.78979880.581114.5776 9888.63110.1864
 9904.73100.91159916.805  93.1719936.87681.003139940.82678.901479948.72475.39405
9956.62372.361469988.02859.397439993.92156.122189996.11755.164719999.81854.80865
10011.4856.1861910031.8358.0621710047.7257.90259 10057.858.5793310068.5558.91319
 10079.358.8649610090.0659.1157210095.4359.7089810100.8161.5161910109.5464.84676
10117.8267.4624110121.9669.0097110133.0675.5133310142.6781.6111210150.9885.73898
#Mann= 3 , 0 , 0
9849.003    0.12       09849.003    0.12       010150.98    0.12       0
#XS Ineff= 2 , 0
       0                10063.74       0
Bank Sta=9849.003,10150.98
Exp/Cntr=0.3,0.1

Type RM Length L Ch R = 1 ,1737.093,126.559100,126.559100,126.559100
XS GIS Cut Line= 2
1251452.40723741 835736.665662841251307.00793186835901.596218407
#Sta/Elev= 30
9934.62673.114069940.42770.805089945.38869.123279957.05866.057879965.80663.43572
 9970.1861.955969975.15659.899819987.674 54.14699990.03953.186819992.04852.53038
    999551.778619999.96251.29683 10000.851.3048610013.9253.1078510022.6654.71773
10027.0455.1696310040.1655.0419110054.5453.6765110062.0352.78142 10066.452.58849
10079.3452.8218310094.2254.2337810097.0254.3904610105.76 54.449610114.5155.16401
10119.03 55.990510133.9162.4260310138.8864.7789910145.1368.22613 10154.573.07143
#Mann= 3 , 0 , 0
9934.626    0.12       09934.626    0.12       0 10154.5    0.12       0
#XS Ineff= 2 , 0
       0                10089.49       0
Bank Sta=9934.626,10154.5
Exp/Cntr=0.3,0.1

Type RM Length L Ch R = 1 ,1610.534,183.209200,183.209200,183.209200
XS GIS Cut Line= 2
1251385.13293186835621.6483017651251209.35168186835828.896565631
#Sta/Elev= 30
 9875.0480.575819878.40778.614179884.44574.495979893.04969.175389897.35166.98615
9905.95563.017219910.25761.214719918.86158.467999927.46555.416869931.76754.09611
9936.06953.035169939.27352.568659954.48951.07346 9979.8547.488629984.92246.52454
9989.99445.131989996.29742.1944810000.1442.02973 10004.9 42.7921 10009.2 44.2099
 10013.545.1425310020.4346.50465 10025.547.1095210047.9246.4386510069.4347.14067
10086.3646.6686410095.2446.8418210099.5448.1089510121.8757.9065710146.7969.33623
#Mann= 3 , 0 , 0
 9875.04    0.12       0 9875.04    0.12       010146.79    0.12       0
#XS Ineff= 2 , 0
       0                 10102.9       0
Bank Sta=9875.04,10146.79
Exp/Cntr=0.3,0.1

Type RM Length L Ch R = 1 ,1427.325,123.126400,123.126400,123.126400
XS GIS Cut Line= 2
1251270.19084062835506.8479163751251095.41939019 835736.66566285
#Sta/Elev= 30
9948.84252.623799952.25451.082169957.67448.959919961.93946.848649970.18344.25425
9973.93443.199329984.77441.29797 9986.6740.541169994.91338.7999110003.1636.49588
10007.2836.56857 10011.437.3889310015.5237.8520810023.7738.0246610033.5538.69234
10052.6238.9613910060.8638.1875510085.5937.8296910102.08 37.121910122.6938.22777
10139.1738.7761910152.7939.1688510169.05 39.172910184.5140.1289410192.7639.76823
10196.8840.3810510209.2443.7855410212.4145.1655210229.8555.4485910237.5760.24254
#Mann= 3 , 0 , 0
9948.842    0.12       09948.842    0.12       010237.57    0.12       0
#XS Ineff= 2 , 0
       0                10123.14       0
Bank Sta=9948.842,10237.57
Exp/Cntr=0.3,0.1

Type RM Length L Ch R = 1 ,1304.199,190.744100,190.744100,190.744100
XS GIS Cut Line= 2
1251207.18154296835400.2941350641251024.88987628835648.775037855
#Sta/Elev= 30
9863.94952.724259871.84949.668329895.09841.478119903.23639.655139907.30538.50869
9910.67437.298929919.51234.591519923.58133.844699935.78932.565399947.99632.52142
9966.13931.270419971.68631.279069977.23231.553639984.61731.506919988.325 30.7733
9992.75529.615029996.82428.883219999.41828.9060310009.03 29.8566 10021.630.65127
10033.4530.3082410043.7930.8021710054.8831.5921610077.0732.4142310094.4833.59611
10110.7635.1914110115.8935.8293110126.9937.5901910139.2439.9096710172.1348.54027
#Mann= 3 , 0 , 0
9863.949    0.12       09863.949    0.12       010172.13    0.12       0
#XS Ineff= 2 , 0
       09941.914        10044.09       0
Bank Sta=9863.949,10172.13
Exp/Cntr=0.3,0.1

Type RM Length L Ch R = 1 ,1113.455,178.764600,178.764600,178.764600
XS GIS Cut Line= 2
1251111.69543183835261.4052461831250878.40550131835526.162190631
#Sta/Elev= 30
9759.02756.658779780.84143.528699785.428 40.98439798.33234.699479807.07730.92664
9815.82327.539619820.196 26.38239828.94124.791849835.05424.132239849.94223.83431
9863.92322.975449869.79222.814549907.65123.896389916.39723.973689929.34323.74634
9973.243 24.07799978.96923.758949986.36123.082989990.73422.406899999.47920.55756
10003.7821.0939710016.9723.4667510021.3423.9303810051.9525.0737510063.3325.83568
 10068.326.3884610086.9330.5217110091.31 31.701410104.4335.99317 10111.938.79002
#Mann= 3 , 0 , 0
9759.027    0.12       09759.027    0.12       0 10111.9    0.12       0
#XS Ineff= 2 , 0
       09894.582        10051.36       0
Bank Sta=9759.027,10111.9
Exp/Cntr=0.3,0.1

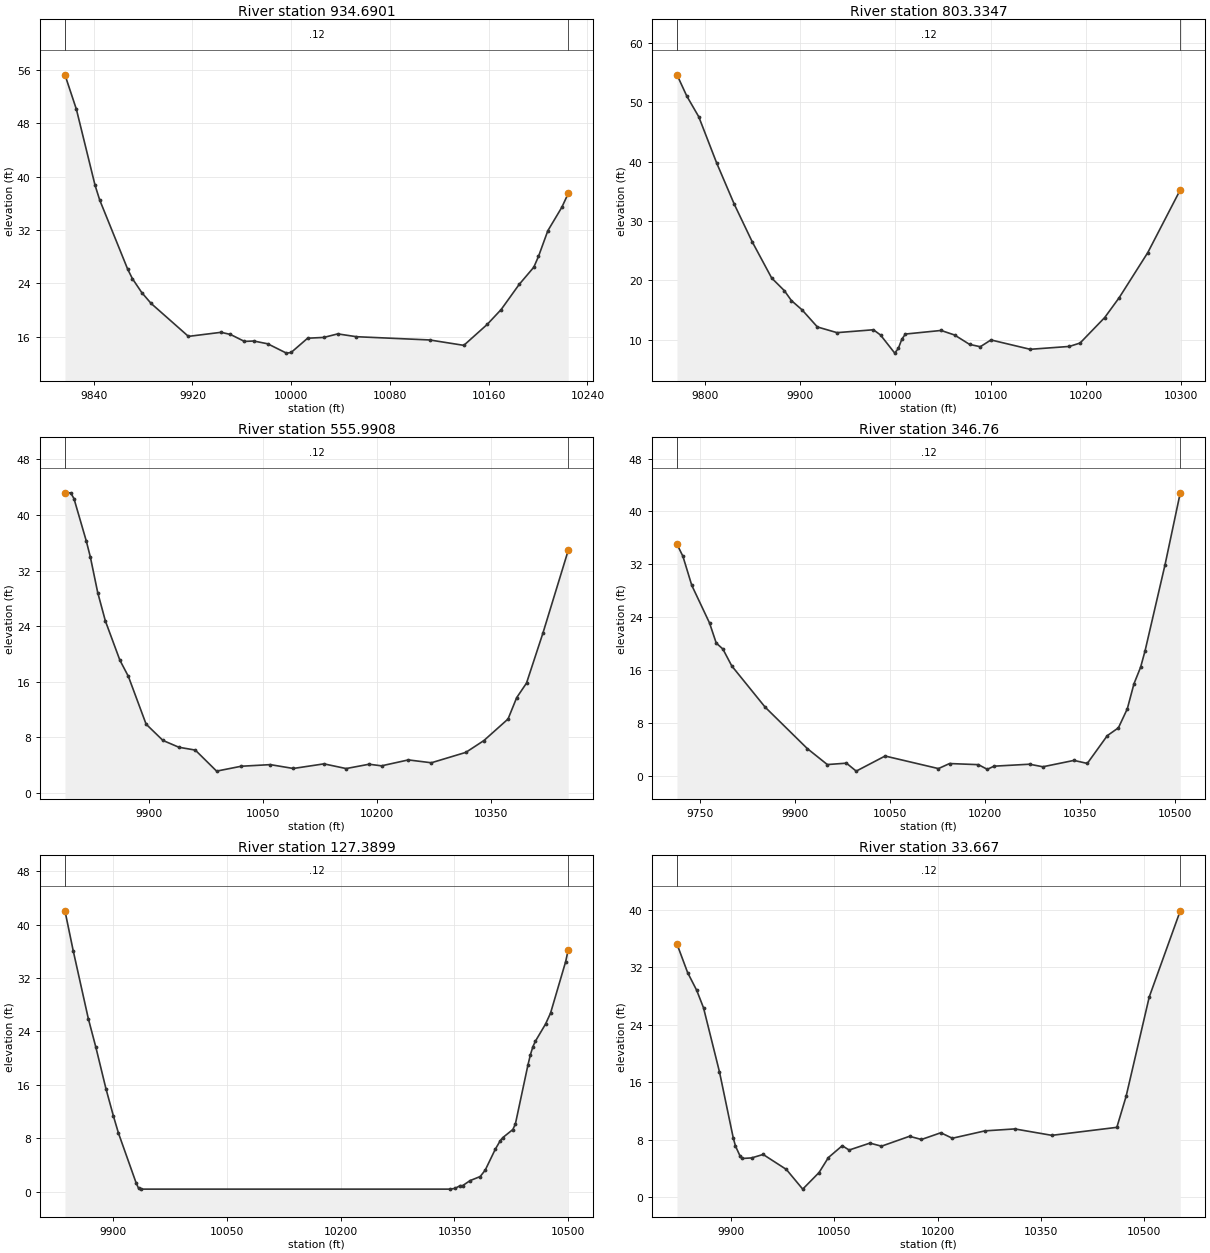
Type RM Length L Ch R = 1 ,934.6901,131.355400,131.355400,131.355400
XS GIS Cut Line= 2
 1251056.3568902835193.0458711831250702.62425128835395.953857288
#Sta/Elev= 30
 9816.65 55.22959825.92750.065429841.05638.689249844.83836.481269867.53226.11736
9871.31424.722399878.87922.641349886.44321.016689916.70216.081169943.17816.69194
9950.74216.371269962.08915.329799969.65415.38874    998114.967769996.12913.57523
9999.91213.66977 10013.3 15.808810026.3915.9256110037.7316.4553810052.8616.03269
10112.2115.5460110139.8614.7393110158.7717.8644910170.1120.0993210184.7423.86535
10196.5926.4396610200.3728.0530310207.9431.8952710219.2835.4036210224.4537.46793
#Mann= 3 , 0 , 0
 9816.65    0.12       0 9816.65    0.12       010224.45    0.12       0
#XS Ineff= 2 , 0
       09943.215                       0
Bank Sta=9816.65,10224.45
Exp/Cntr=0.3,0.1

Type RM Length L Ch R = 1 ,803.3347,247.343900,247.343900,247.343900
XS GIS Cut Line= 2
1251061.78223741835056.3271211981250598.45758465 835309.14830175
#Sta/Elev= 30
9770.98654.618749781.23651.043479793.80947.552329812.49639.797999831.18432.76694
9849.87126.480619870.27820.373699883.50918.254269890.98416.575429902.19615.00176
9918.22412.126979938.77211.167139976.94611.654069984.42110.774049999.3717.716221
10003.118.50862210006.8510.0809310010.58 10.932210047.96 11.537710062.0610.77412
10077.869.18833710089.078.79407710100.289.938012 10141.48.36132310182.518.844909
10193.72 9.41557 10219.613.7196410234.83 17.080510264.7324.65564 10298.835.22762
#Mann= 3 , 0 , 0
9770.986    0.12       09770.986    0.12       0 10298.8    0.12       0
#XS Ineff= 2 , 0
       09961.159                       0
Bank Sta=9770.986,10298.8
Exp/Cntr=0.3,0.1

Type RM Length L Ch R = 1 ,555.9908,209.230800,209.230800,209.230800
XS GIS Cut Line= 2
1250954.95727247834766.8033740821250524.40171692835270.275596291
#Sta/Elev= 30
9788.95743.160139796.483 43.1938  9800.842.370929816.95436.285219822.38533.94801
9832.09828.815569842.19424.718629861.23719.082149872.48216.728079895.7729.857683
9917.9147.5120989938.9416.5279749960.5266.1197159988.5863.08711110020.963.790515
10059.264.02361110089.553.47007710129.934.134415 10159.13.45737510189.324.081386
10205.653.84945810240.994.70363510271.27 4.2915110316.71 5.7915510340.417.490173
10372.2310.5999410383.5813.6737210396.5315.7722810418.1222.9728710451.4234.89016
#Mann= 3 , 0 , 0
9788.957    0.12       09788.957    0.12       010451.42    0.12       0
#XS Ineff= 2 , 0
       0                10318.54       0
Bank Sta=9788.957,10451.42
Exp/Cntr=0.3,0.1

Type RM Length L Ch R = 1 ,  346.76,219.370100,219.370100,219.370100
XS GIS Cut Line= 2
1250757.04060584834534.164485186 1250472.3183836835277.220040724
#Sta/Elev= 30
9712.88635.030439722.203 33.22489736.25728.814519764.36523.110879774.90520.08724
9785.44519.175189799.49916.618969852.201 10.38619918.9564.1081969950.5771.691504
 9980.821.9022449996.2520.69684110041.932.98282710126.251.08146310143.821.844573
10189.491.67677810203.54 0.9683410214.091.445873 10270.31.74319610291.381.356044
10340.572.31935910361.651.86165910393.276.06717910410.847.25076910424.8910.12292
10435.4313.9203210445.9716.43234   1045318.9145610484.6231.9633110508.6242.82162
#Mann= 3 , 0 , 0
9712.886    0.12       09712.886    0.12       010508.62    0.12       0
#XS Ineff= 2 , 0
       0                10289.48       0
Bank Sta=9712.886,10508.62
Exp/Cntr=0.3,0.1

Type RM Length L Ch R = 1 ,127.3899,93.722900,93.722900,93.722900
XS GIS Cut Line= 2
1250458.41128832834617.3080239591250372.78608784835274.609565169
#Sta/Elev= 30
9836.951 42.06779847.90236.046089867.75325.898839877.67921.614759890.913 15.4262
9900.83911.291539907.4568.7440799930.6161.3192779933.9240.4779059937.2330.360892
10344.180.360892 10350.80.47225610357.420.88025810360.730.88459210370.651.643366
10383.89 2.24742 10390.53.20761210403.746.33498510410.367.62948110413.668.082579
 10426.99.29427410430.2110.1105310446.7518.9499810450.0620.5144510453.3721.72843
10456.6822.5469710469.9125.0898710476.5326.7338910496.3834.4216710499.8136.21163
#Mann= 3 , 0 , 0
9836.951    0.12       09836.951    0.12       010499.81    0.12       0
#XS Ineff= 2 , 0
       0                10114.72       0
Bank Sta=9836.951,10499.81
Exp/Cntr=0.3,0.1

Type RM Length L Ch R = 1 ,  33.667,0.000000,0.000000,0.000000
XS GIS Cut Line= 6
1250317.64069059834629.2259589731250329.94335085834728.983147323
1250363.69790787834878.4004361181250330.71179676834999.928213909
1250191.82290787835190.9004361181250216.12846339835302.011547223
#Sta/Elev= 30
9822.12735.243389837.54331.268549850.72728.795229860.615 26.35789883.74117.44052
9903.6618.2723769906.9817.1033079913.6215.7181729916.9415.383079  9930.35.458712
9947.0745.9405979980.7583.854171 10004.51.112212 10028.23.42398810041.745.509981
10061.867.158228 10071.86.55566910101.957.52133710118.757.09321110159.398.469353
10176.748.02633310204.838.962656 10221.5 8.1994210268.819.22584310312.059.496813
10365.868.60280510460.159.71680710473.5814.0319510507.1627.8785110552.1339.87082
#Mann= 3 , 0 , 0
9822.127    0.12       09822.127    0.12       010552.13    0.12       0
#XS Ineff= 2 , 0
       0                10050.33       0
Bank Sta=9822.127,10552.13
Exp/Cntr=0.3,0.1